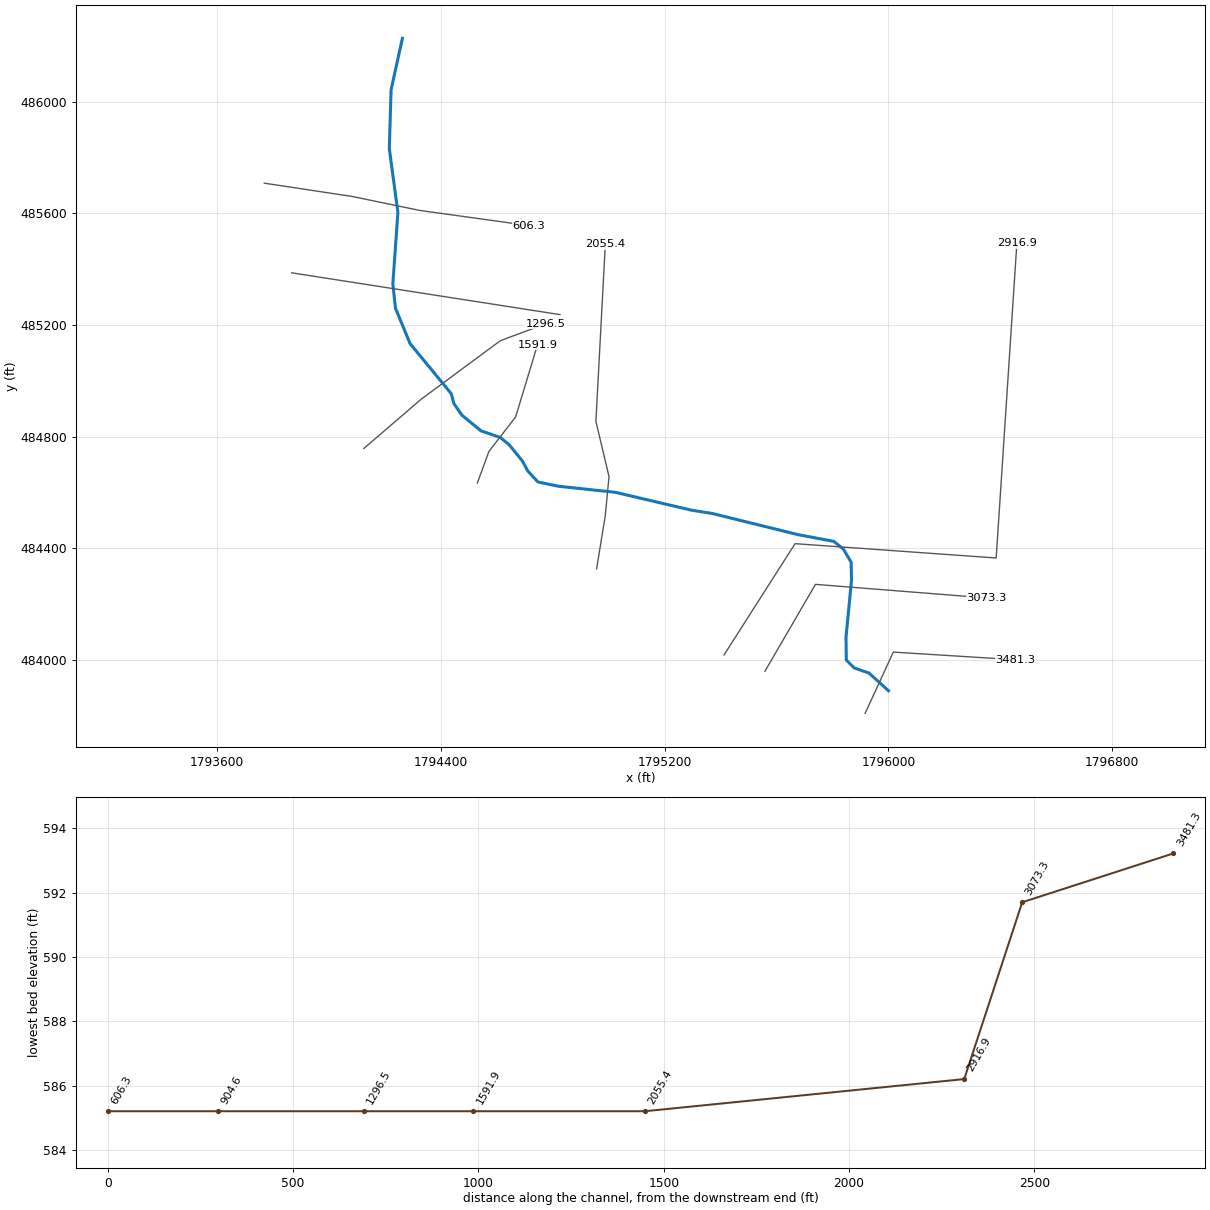
--- VENABLEBR.prj (project) ---

Proj Title=VENABLEBR
Current Plan=p01
Default Exp/Contr=0,0
English Units
Geom File=g01
Flow File=f01
Plan File=p01
BEGIN DESCRIPTION:
END DESCRIPTION:
DSS Export Rating Curves= 0
DSS Export Rating Curve Sorted= 0
DSS Export Volume Flow Curves= 0
DXF OffsetX= 0
DXF OffsetY= 0
DXF ScaleX= 0
DXF ScaleY= 0

--- VENABLEBR.p01 (plan) ---

Plan Title=Floodplain
Program Version=4.00
Geom File=g01
Flow File=f01
K Sum by GR=0
Std Step Tol=0.01
Critical Tol=0.01
Num of Std Step Trials=20
Max Error Tol=0.3
Flow Tol Ratio=0.001
Split Flow NTrial=30
Split Flow Tol=0.02
Split Flow Ratio=0.02
Log Output Level=0
Friction Slope Method=1
Unsteady Friction Slope Method=2
Unsteady Bridges Friction Slope Method=1
Global Log Level=0
CheckData=False
Run HTab=0
Run UNet=0
Run PostProcess=0
UNET Theta=0
UNET Theta Warmup=0
UNET ZTol=0
UNET ZSATol=0
UNET MxIter=0
UNET MaxInSteps=0
UNET DtIC=0
UNET DtMin=0
UNET MaxCRTS=0
UNET WFStab=0
UNET SFStab=0
UNET WFX=0
UNET SFX=0
UNET DSS MLevel=0
UNET DZMax Abort=0
UNET Convert EG Bridges=0
UNET Use Existing IB Tables=0
UNET Froude Limit=0
UNET Froude Power=0
Write IC File=0
Echo Input=False
Echo Output=False
Write Detailed=0

--- VENABLEBR.f01 (steady flow) ---

Flow Title=NFF Regression Equation
Program Version=4.10
Number of Profiles= 1
Profile Names=P100yr
River Rch & RM=VENABLEBR,Main            ,3481.3
699.6195
River Rch & RM=VENABLEBR,Main            ,3073.3
1105.118
Boundary for River Rch & Prof#=VENABLEBR,Main            , 1
Up Type= 0
Dn Type= 3
Dn Slope=0.0005
DSS Import GetInterval= 0
DSS Import GetPeak= 0
DSS Import FillOption= 0

--- VENABLEBR.g01 (geometry) ---

Geom Title=USGS 10m DEM
Program Version=4.10

River Reach=VENABLEBR       ,Main
Reach XY= 30
     1796000.553       483889.78      1795930.53      483953.248
     1795877.917      483971.335     1795849.705      483999.546
      1795848.62      484080.927     1795868.152       484284.92
     1795867.067      484350.024     1795838.855      484397.767
     1795805.218      484424.894     1795675.598      484449.339
      1795371.19       484524.72      1795296.32      484536.656
     1795023.968      484600.675      1794821.06      484622.376
     1794747.275      484637.567     1794710.383      484677.715
     1794691.936      484712.437     1794644.193      484771.031
     1794612.726      484797.072     1794543.282      484820.944
     1794474.922      484877.368     1794446.711        484918.6
     1794436.945      484954.407      1794289.81      485133.661
     1794237.726      485260.397     1794228.329      485347.504
     1794246.407      485604.147     1794215.621      485832.081
     1794222.101      486043.383     1794262.523      486227.231

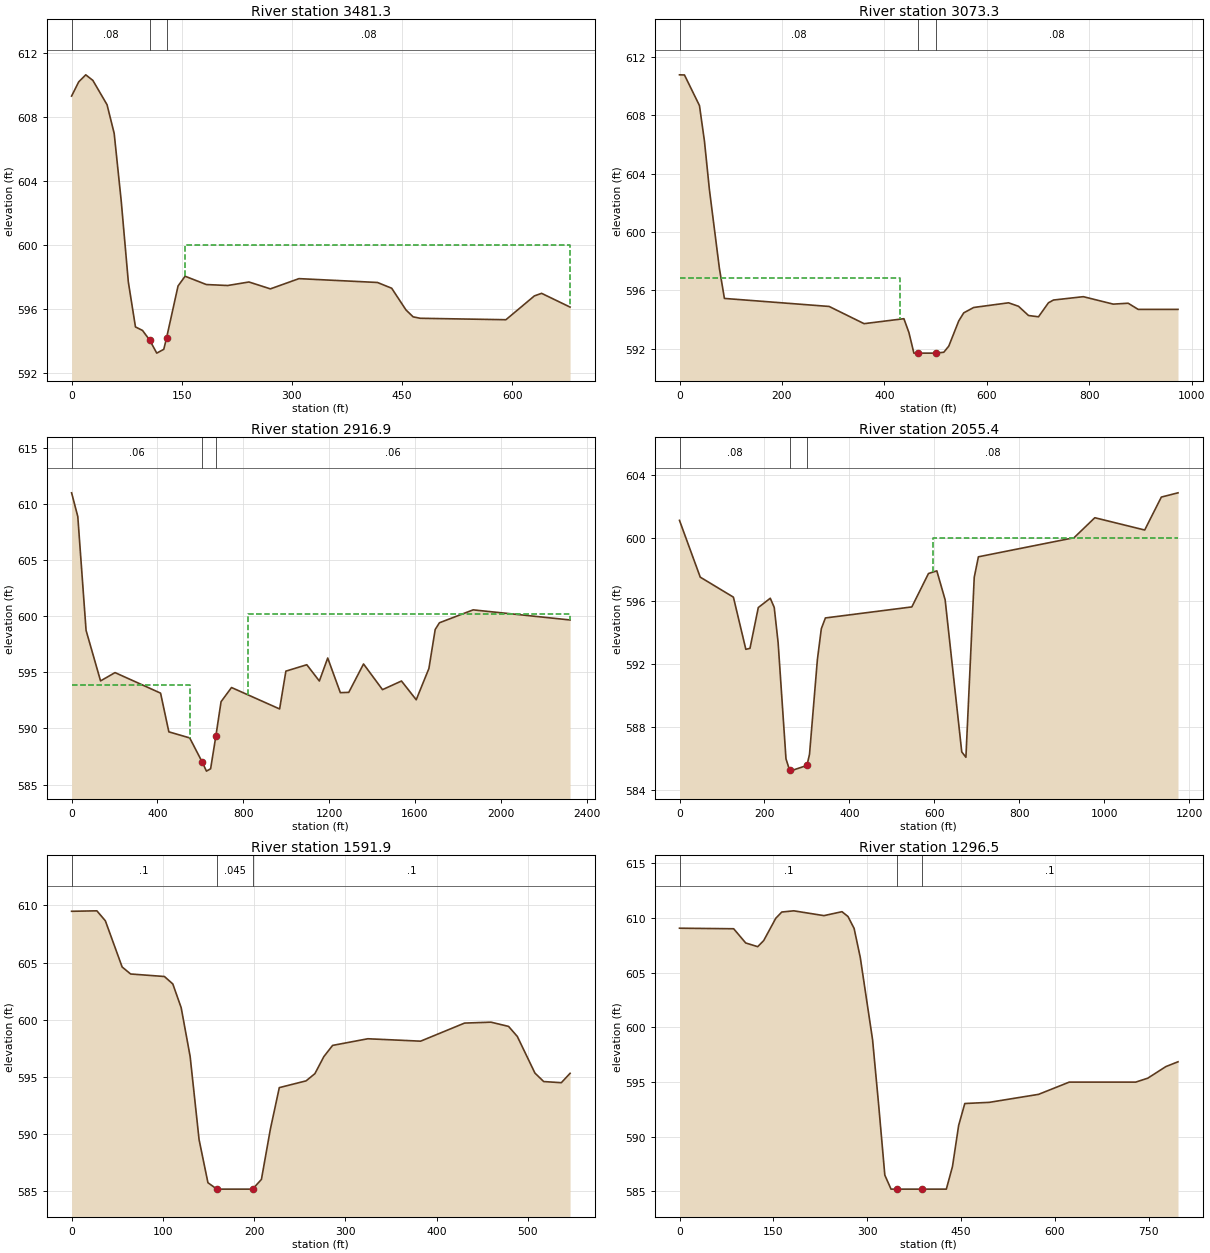
Type RM Length L Ch R = 1 ,3481.3  ,436.6,408,379.3
XS GIS Cut Line= 3
     1795916.902      483808.643     1796017.776      484028.193
     1796454.333      484000.849
#Sta/Elev= 30
       0   609.3     9.7  610.19    19.3  610.63      29  610.28    48.3  608.76
      58  606.97    67.6  602.74    77.3  597.67      87  594.86    96.6  594.64
   106.3  594.04     116  593.22   125.6  593.46   129.4  594.18     145  597.42
   154.6  598.03   183.6  597.51   212.6  597.45   241.6  597.67   270.8  597.24
   309.7  597.88   416.6  597.64     436  597.28   455.5  595.92   465.2  595.49
   474.9   595.4   591.6  595.31   630.4   596.8   640.2  596.96     679   596.1
#Mann= 3 , 0 , 0
       0     .08       0   106.3    .045       0   129.4     .08       0
#XS Ineff= 2 , 0
       0                   154.6       0     600
Permanent Ineff=
       F       F
Bank Sta=106.3,129.4
XS Rating Curve= 0 ,0
Exp/Cntr=0.3,0.1

Type RM Length L Ch R = 1 ,3073.3  ,192,156.4,151.3
XS GIS Cut Line= 3
       1795558.5      483959.182     1795739.384      484270.883
     1796350.496      484222.271
#Sta/Elev= 30
       0  610.78     9.7  610.77      39  608.67    48.7  606.24    58.4  602.91
    77.9  597.51    87.7  595.45   292.2   594.9   360.4  593.72   438.2  594.06
     448  593.11   457.7   591.7     465   591.7     500   591.7   516.1  591.76
   525.8  592.18   545.3  593.91     555  594.46   574.5  594.83   642.6  595.15
     662  594.91   681.5  594.28     701  594.19   720.4  595.15   730.2  595.34
   788.5  595.57   846.9  595.06   876.1  595.12   895.6   594.7   973.4   594.7
#Mann= 3 , 0 , 0
       0     .08       0     465    .045       0     500     .08       0
#XS Ineff= 2 , 0
          431.36  596.82
Permanent Ineff=
       F       F
Bank Sta=465,500
XS Rating Curve= 0 ,0
Exp/Cntr=0.3,0.1

Type RM Length L Ch R = 1 ,2916.9  ,790.1,861.5,901.9
XS GIS Cut Line= 4
     1795412.666       484018.21     1795666.468      484416.716
     1796385.538      484365.354     1796459.523      485492.295
#Sta/Elev= 30
       0     611    28.9  608.89    67.5  598.74     135  594.24   202.5  594.98
   414.6  593.15   453.2   589.7   550.4  589.16   608.8     587   628.3   586.2
   647.8  586.41     672589.2979   696.5  592.39   745.2  593.65   969.3  591.74
   998.5  595.11    1096  595.68  1154.4  594.23  1193.4  596.28  1252.3  593.19
  1291.6  593.22  1360.3  595.75  1448.7  593.46  1537.1  594.23  1605.8  592.56
  1664.8  595.34  1694.2  598.82  1713.9  599.42    1871  600.57  2322.7  599.67
#Mann= 3 , 0 , 0
       0     .06       0   608.8    .045       0     672     .06       0
#XS Ineff= 2 , 0
          550.64   593.9  823.74          600.23
Permanent Ineff=
       F       F
Bank Sta=608.8,672
XS Rating Curve= 0 ,0
Exp/Cntr=0.3,0.1

Type RM Length L Ch R = 1 ,2055.4  ,476.9,463.6,450.3
XS GIS Cut Line= 5
     1794956.919      484326.496     1794988.169      484519.204
      1795001.19      484657.225     1794954.315      484855.142
     1794988.169      485490.559
#Sta/Elev= 30
       0  601.11    48.8  597.51   126.9  596.24   156.2  592.93   165.9  592.99
   185.5  595.58   213.7  596.17     223  595.59   232.2  593.35   250.7  585.98
     259585.2763   259.9   585.2     300585.5605   306.1  586.27   324.6  592.27
   333.9  594.24   343.5  594.92     547  595.62   586.2  597.74   605.8  597.91
   625.4  596.07   664.5  586.42   674.3  586.08   693.9   597.5   703.7   598.8
   928.8  600.01   977.8  601.28  1095.2   600.5  1134.4  602.59  1173.6  602.86
#Mann= 3 , 0 , 0
       0     .08       0     259    .045       0     300     .08       0
#XS Ineff= 2 , 0
       0                     596       0     600
Permanent Ineff=
       F       F
Bank Sta=259,300
XS Rating Curve= 0 ,0
Exp/Cntr=0.3,0.1

Type RM Length L Ch R = 1 ,1591.9  ,301.3,295.3,289.3
XS GIS Cut Line= 4
     1794530.577      484634.095      1794571.81      484746.942
     1794667.296       484870.64     1794745.421      485128.887
#Sta/Elev= 30
       0  609.48    27.7  609.52      37  608.65    55.4  604.61    64.7     604
   101.7  603.78   110.9  603.13   120.1  601.05   129.9  596.79   139.7  589.52
   149.4  585.76   159.2   585.2   198.3   585.2     208  586.05   217.8  590.44
   227.6  594.07   256.9  594.66   266.6  595.29   276.4  596.78     286  597.76
   324.6  598.34   382.4  598.13   430.6  599.71   459.5  599.79   478.8  599.42
   488.4  598.54   507.7  595.34   517.3   594.6   536.6   594.5   546.2  595.32
#Mann= 3 , 0 , 0
       0      .1       0   159.2    .045       0   198.3      .1       0
Bank Sta=159.2,198.3
XS Rating Curve= 0 ,0
Exp/Cntr=0.3,0.1

Type RM Length L Ch R = 1 ,1296.5  ,409.9,391.9,373.8
XS GIS Cut Line= 4
     1794124.761      484757.793     1794328.754      484933.574
     1794613.043      485144.078     1794775.803      485204.842
#Sta/Elev= 30
       0  609.07    86.6  609.02   105.8  607.72     125  607.38   134.6  607.94
   153.9  609.98   163.5  610.55   182.7  610.66   230.8  610.22   259.7  610.58
   269.3  610.14   279.1  609.05   288.9  606.41   308.6  598.87   318.4  592.86
   328.2  586.48   338.1   585.2   347.9   585.2   387.2   585.2   426.5   585.2
   436.3  587.26   446.2  591.03     456  593.03   495.3  593.14   573.9  593.87
     623  594.99   729.2  594.99   748.5  595.35   777.4  596.41   796.8  596.85
#Mann= 3 , 0 , 0
       0      .1       0   347.9    .045       0   387.2      .1       0
Bank Sta=347.9,387.2
XS Rating Curve= 0 ,0
Exp/Cntr=0.3,0.1

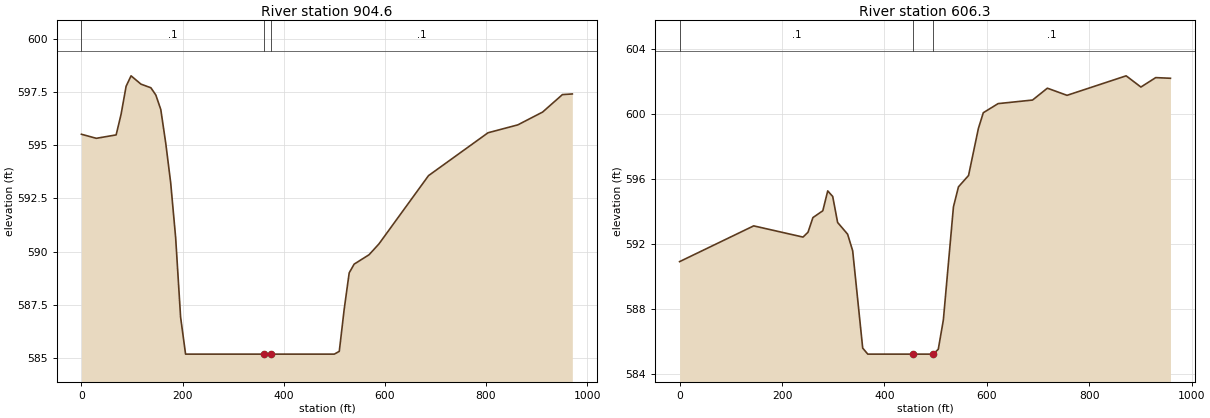
Type RM Length L Ch R = 1 ,904.6   ,299.8,298.3,297.1
XS GIS Cut Line= 2
     1793866.515      485387.133     1794825.716      485237.394
#Sta/Elev= 30
       0  595.51    29.4  595.32    68.6  595.48    78.4  596.45    88.3  597.76
    98.1  598.25   117.7  597.86   137.3  597.69   147.1  597.35   156.9  596.67
   166.7  595.09   176.5  593.23   186.3  590.66   196.1  586.93   205.9   585.2
   360.6   585.2   375.6   585.2   500.1   585.2   509.9  585.33   519.7  587.32
   529.5  589.01   539.3  589.42   568.8  589.86   588.4  590.37   686.4  593.57
   804.1  595.58     863  595.95     912  596.55   951.2  597.37   970.8   597.4
#Mann= 3 , 0 , 0
       0      .1       0   360.6    .045       0   375.6      .1       0
Bank Sta=360.6,375.6
XS Rating Curve= 0 ,0
Exp/Cntr=0.3,0.1

Type RM Length L Ch R = 1 ,606.3   ,606,606.3,606.2
XS GIS Cut Line= 4
     1793768.859      485708.314     1794083.529      485660.571
     1794324.414      485610.658     1794715.039      485556.404
#Sta/Elev= 30
       0  590.89   144.7  593.09   241.1   592.4   250.8   592.7   260.4   593.6
   279.7  594.02   289.3  595.24     299   594.9   308.6   593.3   328.1  592.58
     338  591.56   357.6  585.57   367.5   585.2     456   585.2   495.4   585.2
   505.2   585.5   515.1   587.3   534.8  594.26   544.6  595.49   564.3  596.19
   583.5  599.08   593.1  600.05     622  600.61   689.3  600.83   718.2  601.56
   756.6  601.12   872.1  602.32   900.9  601.63   929.8  602.21   958.6  602.17
#Mann= 3 , 0 , 0
       0      .1       0     456    .045       0   495.4      .1       0
Bank Sta=456,495.4
XS Rating Curve= 0 ,0
Exp/Cntr=0.3,0.1

Chan Stop Cuts=-1
Use User Specified Reach Order=0
Composite Channel Slope=5